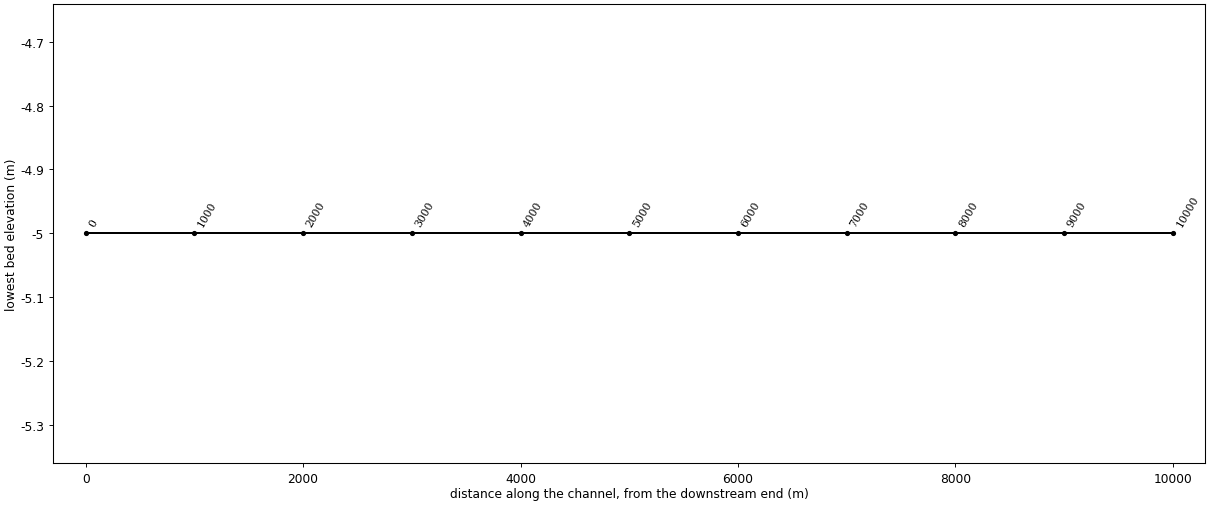
--- simple_reach.prj (project) ---

Proj Title=simple_reach
Current Plan=p03
Default Exp/Contr=0.3,0.1
SI Units
Geom File=g01
Flow File=f01
Unsteady File=u01
QuasiSteady File=q01
Plan File=p01
Plan File=p02
Plan File=p03
Y Axis Title=Elevation
X Axis Title(PF)=Main Channel Distance
X Axis Title(XS)=Station
BEGIN DESCRIPTION:
END DESCRIPTION:
DSS Start Date=01JAN2013
DSS Start Time=0:00
DSS End Date=03JAN2013
DSS End Time=0:30
DSS File=dss
DSS Export Rating Curves= 0
DSS Export Rating Curve Sorted= 0
DSS Export Volume Flow Curves= 0
DXF OffsetX= 0
DXF OffsetY= 0
DXF ScaleX= 1
DXF ScaleY= 10

--- simple_reach.p03 (plan) ---

Plan Title=Plan 03
Program Version=5.06
Short Identifier=Plan 03
Simulation Date=01JAN2013,1:00,03JAN2013,0:30
Geom File=g01
Flow File=u01
Subcritical Flow
K Sum by GR= 0
Std Step Tol= 0.003
Critical Tol= 0.003
Num of Std Step Trials= 20
Max Error Tol= 0.1
Flow Tol Ratio= 0.001
Split Flow NTrial= 30
Split Flow Tol= 0.006
Split Flow Ratio= 0.02
Log Output Level= 0
Friction Slope Method= 1
Unsteady Friction Slope Method= 2
Unsteady Bridges Friction Slope Method= 1
Parabolic Critical Depth
Global Vel Dist= 0 , 0 , 0
Global Log Level= 0
CheckData=True
Encroach Param=-1 ,0,0, 0
Computation Interval=15MIN
Output Interval=15MIN
Instantaneous Interval=15MIN
Mapping Interval=15MIN
Computation Time Step Use Courant=        0
Computation Time Step Use Time Series=    0
Computation Time Step Count To Double=0
Computation Time Step Max Doubling=0
Computation Time Step Max Halving=0
Computation Time Step Residence Courant=0
Run HTab=-1
Run UNet=-1
Run Sediment= 0
Run PostProcess= 0
Run WQNet= 0
Run RASMapper= 0
UNET Theta= 1
UNET Theta Warmup= 1
UNET ZTol= 0.006
UNET ZSATol= 0.006
UNET MxIter= 20
UNET Max Iter WO Improvement= 0
UNET MaxInSteps= 0
UNET DtIC= 0
UNET DtMin= 0
UNET MaxCRTS= 20
UNET WFStab= 2
UNET SFStab= 1
UNET WFX= 1
UNET SFX= 1
UNET 1D Methodology=Finite Difference
UNET DSS MLevel= 4
UNET Pardiso=0
UNET DZMax Abort= 30
UNET Use Existing IB Tables=-1
UNET Froude Reduction=False
UNET Froude Limit= 0.8
UNET Froude Power= 4
UNET D1 Cores= 0
UNET D2 Coriolis=0
UNET D2 Cores= 0
UNET D2 Theta= 1
UNET D2 Theta Warmup= 1
UNET D2 Z Tol= 0.003
UNET D2 Volume Tol= 0.003
UNET D2 Max Iterations= 20
UNET D2 Equation= 0
UNET D2 RampUpFraction=0.1
UNET D2 TimeSlices= 1
UNET D2 BCVolumeCheck=0
UNET D1D2 MaxIter= 0
UNET D1D2 ZTol=0.003
UNET D1D2 QTol=0.1
UNET D1D2 MinQTol=0.03
DSS File=dss
Write IC File= 0
Write IC File at Fixed DateTime=0
Write IC File at Sim End=0
Echo Input=False
Echo Parameters=False
Echo Output=False
Write Detailed= 0
HDF Write Warmup=0
HDF Write Time Slices=0
HDF Flush=0
HDF Face Node Velocities=0
HDF Compression= 1
HDF Chunk Size= 1
HDF Spatial Parts= 1
HDF Use Max Rows=0
HDF Fixed Rows= 1
Calibration Method= 0
Calibration Iterations= 20
Calibration Max Change=0.05
Calibration Tolerance=0.2
Calibration Maximum=1.5
Calibration Minimum=0.5
Calibration Optimization Method= 1
WQ AD Non Conservative
WQ ULTIMATE=-1
WQ Max Comp Step=1HOUR
WQ Output Interval=15MIN
WQ Output Selected Increments= 0
WQ Output face flow=0
WQ Output face velocity=0
WQ Output face area=0
WQ Output face dispersion=0
WQ Output cell volume=0
WQ Output cell surface area=0
WQ Output cell continuity=0
WQ Output cumulative cell continuity=0
WQ Output face conc=0
WQ Output face dconc_dx=0
WQ Output face courant=0
WQ Output face peclet=0
WQ Output face adv mass=0
WQ Output face disp mass=0
WQ Output cell mass=0
WQ Output cell source sink temp=0
WQ Output nsm pathways=0
WQ Output nsm derived pathways=0
WQ Output MaxMinRange=-1
WQ Daily Max Min Mean=-1
WQ Daily Range=0
WQ Daily Time=0
WQ Create Restart=0
WQ Fixed Restart=0
WQ System Summary=0
WQ Write To DSS=0
WQ Use Fixed Temperature=0
WQ StartDate=01JAN2013
WQ StartTime=1:00
WQ EndDate=03JAN2013
WQ EndTime=0:00
Sorting and Armoring Iterations= 10
XS Update Threshold= 0.02
Bed Roughness Predictor= 0
Hydraulics Update Threshold= 0.02
Energy Slope Method= 1
Volume Change Method= 1
Sediment Retention Method= 0
XS Weighting Method= 0
Number of US Weighted Cross Sections= 1
Number of DS Weighted Cross Sections= 1
Upstream XS Weight=0
Main XS Weight=1
Downstream XS Weight=0
Number of DS XS's Weighted with US Boundary= 1
Upstream Boundary Weight= 1
Weight of XSs Associated with US Boundary= 0
Number of US XS's Weighted with DS Boundary= 1
Downstream Boundary Weight= 0.5
Weight of XSs Associated with DS Boundary= 0.5
Percentile Method= 0
Sediment Output Level= 3
Mass or Volume Output= 0
Output Increment Type= 1
Profile and TS Output Increment= 1
XS Output Flag= 0
XS Output Increment= 10
Write Gradation File= 0
Read Gradation Hotstart= 0
Write HDF5 File= 1
Write Binary Output= 1
Write DSS Sediment File= 0
SV Curve= 0
Specific Gage Flag= 0

--- simple_reach.p01 (plan) ---

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Plan Title=pest_plan
Short Identifier=test_plan
Geom File=g01
Computation Interval=1MIN
Output Interval=1HOUR
Instantaneous Interval=1HOUR
Mapping Interval=1HOUR
Run HTab= 0
Run UNet= 0

--- simple_reach.p02 (plan) ---

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Plan Title=test_plan
Short Identifier=tp1
Geom File=g01
Flow File=f01
Computation Interval=1MIN
Output Interval=1HOUR
Instantaneous Interval=1HOUR
Mapping Interval=1HOUR
Run HTab= 0
Run UNet= 0

--- simple_reach.f01 (steady flow) ---

Flow Title=steady_betty
Program Version=5.06
BEGIN FILE DESCRIPTION:
steady_betty
END FILE DESCRIPTION:
Number of Profiles= 1
Profile Names=PF 1
River Rch & RM=river1,reach1          ,10000
       1
Boundary for River Rch & Prof#=river1,reach1          , 1
Up Type= 0
Dn Type= 1
Dn Known WS=0
DSS Import GetInterval= 0
DSS Import GetPeak= 0
DSS Import FillOption= 0

--- simple_reach.u01 (unsteady flow) ---

Flow Title=block_inflow
Program Version=5.06
Use Restart= 0
Initial Flow Loc=river1          ,reach1          ,10000   ,100
Boundary Location=river1          ,reach1          ,10000   ,        ,                ,                ,                ,
Interval=15MIN
Flow Hydrograph= 191
     100     100     100     100     100     100     100     100     100     100
     100     100     100     100     100     100     100     100     100     100
     100     100     100     100     100     100     100     100     100     100
     100     100     100     100     100     100     100     100     100     100
     100     100     100     100     100     100     100     100     100     100
     100     100     100     100     100     100     100     100     100     100
     100     100     100     100     100     100     100     100     100     100
     100     100     100     100     100     100     100     100     100     100
     500     500     500     500     500     500     500     500     500     500
     500     500     500     500     500     500     500     500     500     500
     500     500     500     500     500     500     500     500     500     500
     500     500     500     500     500     500     500     500     500     500
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Use DSS=False
Use Fixed Start Time=True
Fixed Start Date/Time=01JAN2013,1:00
Is Critical Boundary=False
Boundary Location=river1          ,reach1          ,0       ,        ,                ,                ,                ,
Interval=15MIN
Stage Hydrograph= 191
       0       0       0       0       0       0       0       0       0       0
       0       0       0       0       0       0       0       0       0       0
       0       0       0       0       0       0       0       0       0       0
       0       0       0       0       0       0       0       0       0       0
       0       0       0       0       0       0       0       0       0       0
       0       0       0       0       0       0       0       0       0       0
       0       0       0       0       0       0       0       0       0       0
       0       0       0       0       0       0       0       0       0       0
       0       0       0       0       0       0       0       0       0       0
       0       0       0       0       0       0       0       0       0       0
       0       0       0       0       0       0       0       0       0       0
       0       0       0       0       0       0       0       0       0       0
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Use DSS=False
Use Fixed Start Time=True
Fixed Start Date/Time=01JAN2013,1:00
Is Critical Boundary=False
Boundary Location=river1          ,reach1          ,10000   ,        ,                ,                ,                ,
Boundary Location=river1          ,reach1          ,9000    ,        ,                ,                ,                ,
Boundary Location=river1          ,reach1          ,8000    ,        ,                ,                ,                ,
Boundary Location=river1          ,reach1          ,7000    ,        ,                ,                ,                ,
Boundary Location=river1          ,reach1          ,6000    ,        ,                ,                ,                ,
Boundary Location=river1          ,reach1          ,5000    ,        ,                ,                ,                ,
Boundary Location=river1          ,reach1          ,4000    ,        ,                ,                ,                ,
Boundary Location=river1          ,reach1          ,3000    ,        ,                ,                ,                ,
Boundary Location=river1          ,reach1          ,2000    ,        ,                ,                ,                ,
Boundary Location=river1          ,reach1          ,1000    ,        ,                ,                ,                ,
Boundary Location=river1          ,reach1          ,0       ,        ,                ,                ,                ,

--- simple_reach.g01 (geometry) ---

Geom Title=test_geo
Program Version=5.06

River Reach=river1          ,reach1
Reach XY= 2
-0.10269709543560.601659751037340.449170124481330.60165975103734

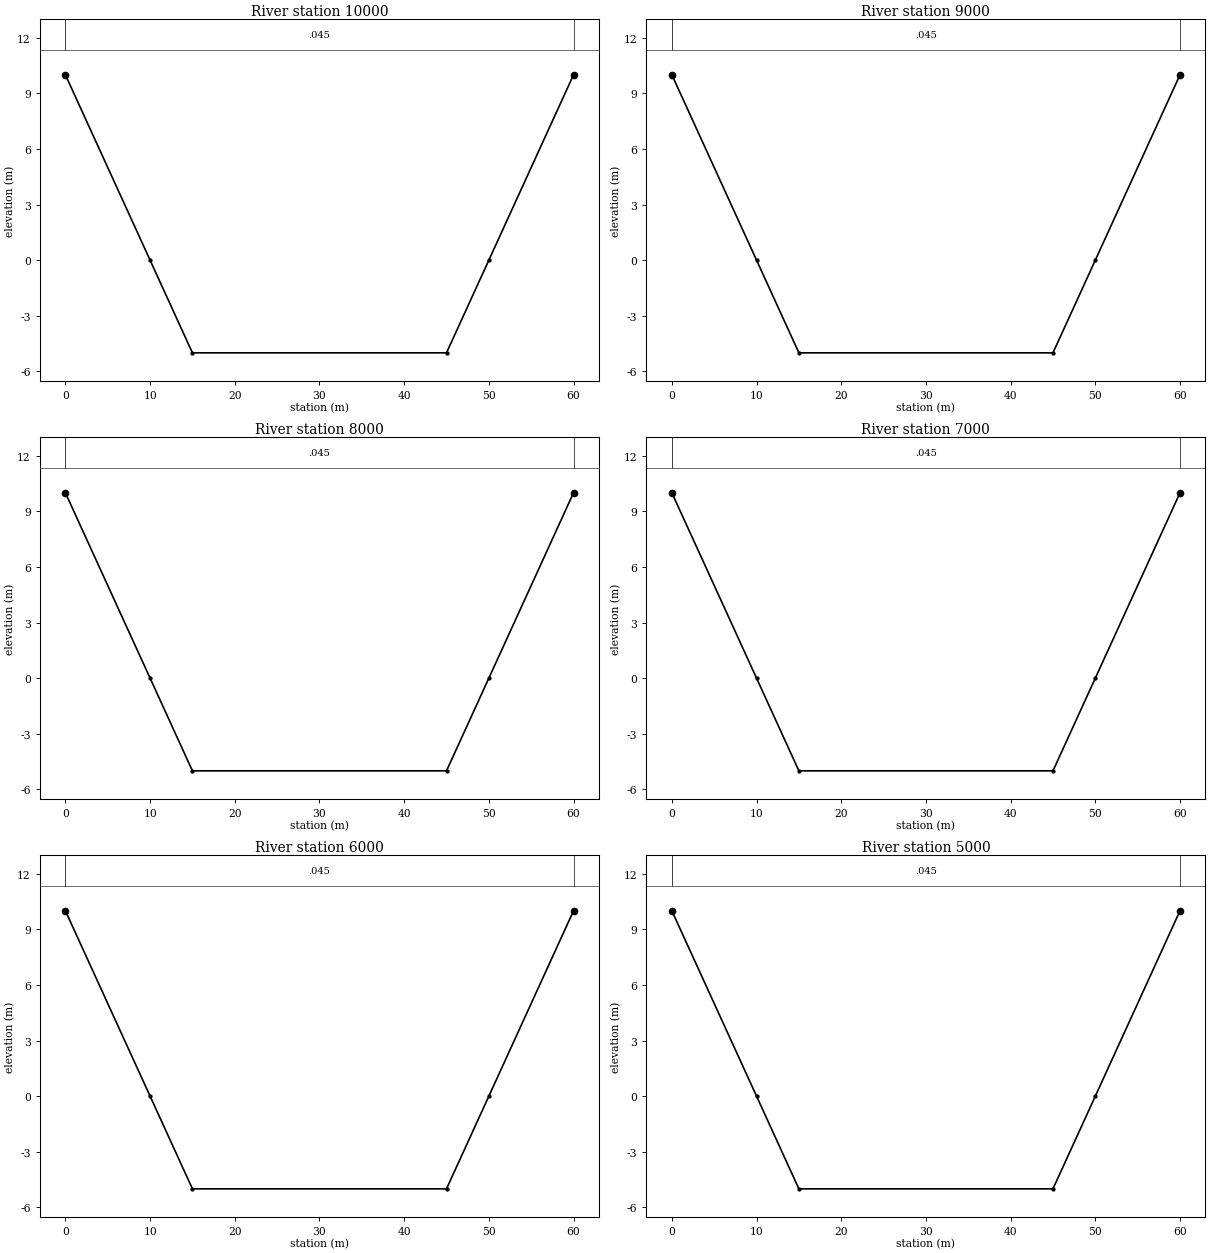
Type RM Length L Ch R = 1 ,10000   ,1000,1000,1000
BEGIN DESCRIPTION:
upstream boundary of
Reach Upstream
END DESCRIPTION:
#Sta/Elev= 6
       0      10      10       0      15      -5      45      -5      50       0
      60      10
#Mann= 3 , 0 , 0
       0    .045       0       0    .045       0      60    .045       0
Bank Sta=0,60
XS Rating Curve= 0 ,0
Exp/Cntr=0.3,0.1

Type RM Length L Ch R = 1 ,9000    ,1000,1000,1000
BEGIN DESCRIPTION:
upstream boundary of
Reach Upstream
END DESCRIPTION:
#Sta/Elev= 6
       0      10      10       0      15      -5      45      -5      50       0
      60      10
#Mann= 3 , 0 , 0
       0    .045       0       0    .045       0      60    .045       0
Bank Sta=0,60
XS Rating Curve= 0 ,0
Exp/Cntr=0.3,0.1

Type RM Length L Ch R = 1 ,8000    ,1000,1000,1000
BEGIN DESCRIPTION:
upstream boundary of
Reach Upstream
END DESCRIPTION:
#Sta/Elev= 6
       0      10      10       0      15      -5      45      -5      50       0
      60      10
#Mann= 3 , 0 , 0
       0    .045       0       0    .045       0      60    .045       0
Bank Sta=0,60
XS Rating Curve= 0 ,0
Exp/Cntr=0.3,0.1

Type RM Length L Ch R = 1 ,7000    ,1000,1000,1000
BEGIN DESCRIPTION:
upstream boundary of
Reach Upstream
END DESCRIPTION:
#Sta/Elev= 6
       0      10      10       0      15      -5      45      -5      50       0
      60      10
#Mann= 3 , 0 , 0
       0    .045       0       0    .045       0      60    .045       0
Bank Sta=0,60
XS Rating Curve= 0 ,0
Exp/Cntr=0.3,0.1

Type RM Length L Ch R = 1 ,6000    ,1000,1000,1000
BEGIN DESCRIPTION:
upstream boundary of
Reach Upstream
END DESCRIPTION:
#Sta/Elev= 6
       0      10      10       0      15      -5      45      -5      50       0
      60      10
#Mann= 3 , 0 , 0
       0    .045       0       0    .045       0      60    .045       0
Bank Sta=0,60
XS Rating Curve= 0 ,0
Exp/Cntr=0.3,0.1

Type RM Length L Ch R = 1 ,5000    ,1000,1000,1000
BEGIN DESCRIPTION:
upstream boundary of
Reach Upstream
END DESCRIPTION:
#Sta/Elev= 6
       0      10      10       0      15      -5      45      -5      50       0
      60      10
#Mann= 3 , 0 , 0
       0    .045       0       0    .045       0      60    .045       0
Bank Sta=0,60
XS Rating Curve= 0 ,0
Exp/Cntr=0.3,0.1

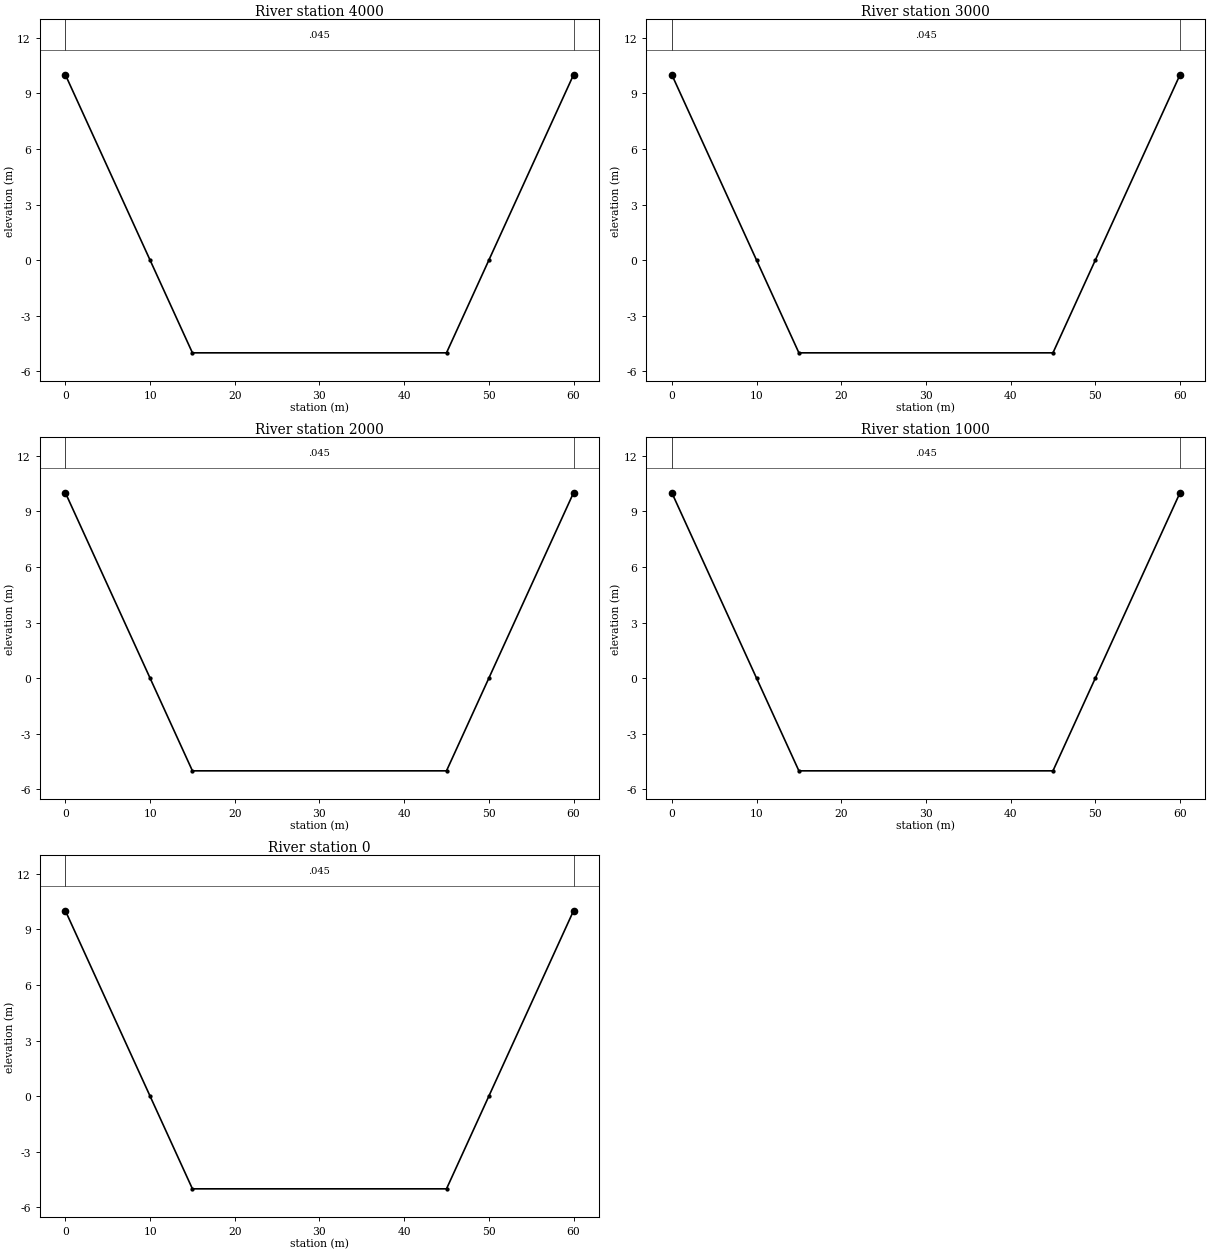
Type RM Length L Ch R = 1 ,4000    ,1000,1000,1000
BEGIN DESCRIPTION:
upstream boundary of
Reach Upstream
END DESCRIPTION:
#Sta/Elev= 6
       0      10      10       0      15      -5      45      -5      50       0
      60      10
#Mann= 3 , 0 , 0
       0    .045       0       0    .045       0      60    .045       0
Bank Sta=0,60
XS Rating Curve= 0 ,0
Exp/Cntr=0.3,0.1

Type RM Length L Ch R = 1 ,3000    ,1000,1000,1000
BEGIN DESCRIPTION:
upstream boundary of
Reach Upstream
END DESCRIPTION:
#Sta/Elev= 6
       0      10      10       0      15      -5      45      -5      50       0
      60      10
#Mann= 3 , 0 , 0
       0    .045       0       0    .045       0      60    .045       0
Bank Sta=0,60
XS Rating Curve= 0 ,0
Exp/Cntr=0.3,0.1

Type RM Length L Ch R = 1 ,2000    ,1000,1000,1000
BEGIN DESCRIPTION:
upstream boundary of
Reach Upstream
END DESCRIPTION:
#Sta/Elev= 6
       0      10      10       0      15      -5      45      -5      50       0
      60      10
#Mann= 3 , 0 , 0
       0    .045       0       0    .045       0      60    .045       0
Bank Sta=0,60
XS Rating Curve= 0 ,0
Exp/Cntr=0.3,0.1

Type RM Length L Ch R = 1 ,1000    ,1000,1000,1000
BEGIN DESCRIPTION:
upstream boundary of
Reach Upstream
END DESCRIPTION:
#Sta/Elev= 6
       0      10      10       0      15      -5      45      -5      50       0
      60      10
#Mann= 3 , 0 , 0
       0    .045       0       0    .045       0      60    .045       0
Bank Sta=0,60
XS Rating Curve= 0 ,0
Exp/Cntr=0.3,0.1

Type RM Length L Ch R = 1 ,0       ,0,0,0
BEGIN DESCRIPTION:
upstream boundary of
Reach Upstream
END DESCRIPTION:
#Sta/Elev= 6
       0      10      10       0      15      -5      45      -5      50       0
      60      10
#Mann= 3 , 0 , 0
       0    .045       0       0    .045       0      60    .045       0
Bank Sta=0,60
XS Rating Curve= 0 ,0
Exp/Cntr=0.3,0.1
LCMann Table=0

Chan Stop Cuts=-1
Use User Specified Reach Order=0
Composite Channel Slope=5